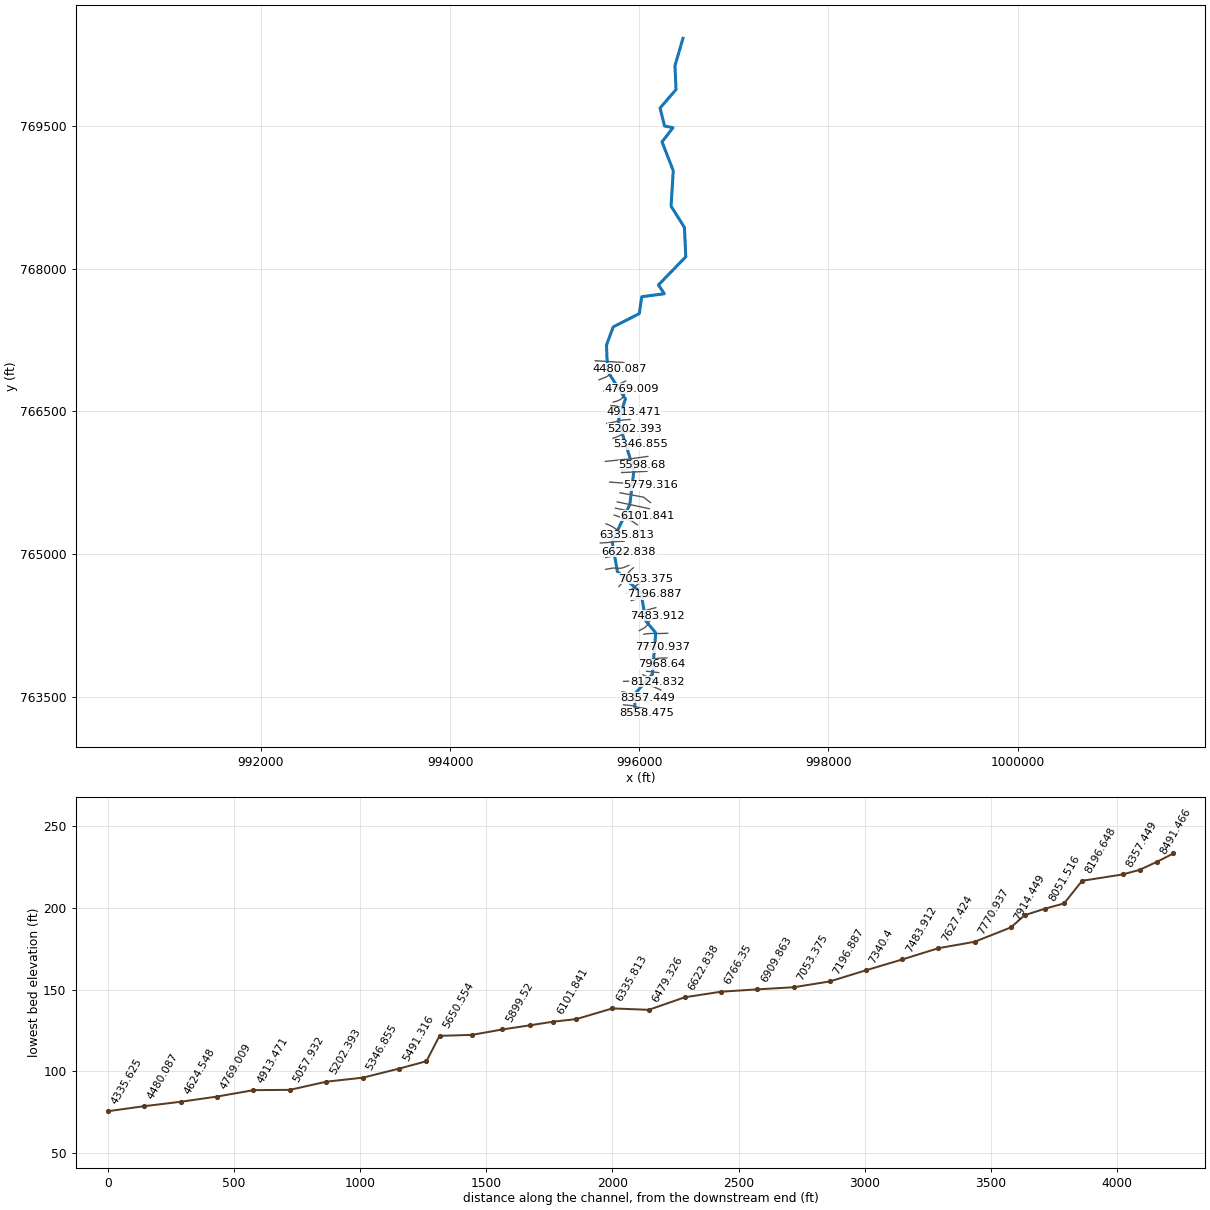
--- 155_ras.prj (project) ---

Proj Title=155
Current Plan=p01
Default Exp/Contr=0.3,0.1
English Units
Geom File=g01
Flow File=f01
Plan File=p01
Y Axis Title=Elevation
X Axis Title(PF)=Main Channel Distance
X Axis Title(XS)=Station
BEGIN DESCRIPTION:
RFD model 155 exported to HEC-RAS
END DESCRIPTION:

--- 155_ras.p01 (plan) ---

Plan Title=Plan 01
Program Version=4.10
Short Identifier=Plan 01
Geom File=g01
Flow File=f01
Subcritical Flow
Calc Critical at every XS
Secant Critical Depth

--- 155_ras.f01 (steady flow) ---

Flow Title=Flow 01
Program Version=5.01
Number of Profiles= 6
Profile Names=10yr,25yr,50yr,100yr,100plus,500yr
River Rch & RM=155,40,8558.475
   89.77  171.41  259.57  357.11  521.38 1189.94
River Rch & RM=155,40,6479.326
   96.26  183.86  278.51  383.21  559.49 1264.56
River Rch & RM=155,40,6335.813
   98.06  187.31  283.76  390.47  570.08 1285.23
River Rch & RM=155,40,6192.301
  117.63  224.94  341.05  469.51  685.49 1506.95
River Rch & RM=155,40,6101.841
  118.21  226.04  342.73  471.83  688.87  1513.4
River Rch & RM=155,40,6010.537
  148.75  284.87  432.43  595.74  869.79 1851.37
River Rch & RM=155,40, 5899.52
  150.38  288.01  437.22  602.38  879.47  1869.2
River Rch & RM=155,40,5779.316
   151.1  289.41  439.35  605.32  883.76  1877.1
River Rch & RM=155,40,5650.554
  156.32  299.47  454.72  626.57  914.79 1933.99
River Rch & RM=155,40,5491.316
  157.57  301.89  458.41  631.67  922.24 1947.62
River Rch & RM=155,40,5346.855
  160.07  306.72  465.78  641.86  937.12 1974.77
River Rch & RM=155,40,5202.393
  160.96  308.44   468.4  645.49  942.42 1984.44
River Rch & RM=155,40,5057.932
  161.85  310.15  471.03  649.12  947.71 1994.08
River Rch & RM=155,40,4913.471
  163.45  313.24  475.74  655.63  957.23 2011.39
River Rch & RM=155,40,4769.009
   167.5  321.07  487.71   672.2  981.41 2055.38
River Rch & RM=155,40,4624.548
  168.36  322.74  490.27  675.76  986.61 2064.89
River Rch & RM=155,40,4480.087
  273.95  526.25  800.85 1104.82 1613.03  3153.9
River Rch & RM=155,40,4335.625
  274.87  528.05  803.63 1108.68 1618.67 3163.55
River Rch & RM=155,40,4115.967
  280.73  539.47  821.19 1133.09 1654.31 3224.41
River Rch & RM=155,40,3894.277
  283.19  544.26  828.56 1143.33 1669.27  3249.9
River Rch & RM=155,40,3672.587
  289.98  557.47  848.84  1171.5  1710.4 3319.59
River Rch & RM=155,40,3450.897
  297.47  572.06  871.27 1202.67  1755.9 3396.53
Boundary for River Rch & Prof#=155,40,1
Up Type= 0
Dn Type= 2
Boundary for River Rch & Prof#=155,40,2
Up Type= 0
Dn Type= 2
Boundary for River Rch & Prof#=155,40,2
Up Type= 0
Dn Type= 2
Boundary for River Rch & Prof#=155,40,2
Up Type= 0
Dn Type= 2
Boundary for River Rch & Prof#=155,40,2
Up Type= 0
Dn Type= 2
Boundary for River Rch & Prof#=155,40,2
Up Type= 0
Dn Type= 2

--- 155_ras.g01 (geometry) ---

Geom Title=155
Program Version=4.10

River Reach=155,40
Reach XY= 30
995951.906614418763328.637049757995954.328975084763529.692985179
 996138.42838583763734.382461606996174.022072139764168.821601884
996068.506458826  764295.9333501996019.118965258764589.453675324
995769.018384006764813.544139076995713.304088648765124.817484864
995899.825860062765520.873454039995943.428352078765878.171652526
995777.496646339766401.401556751995853.435752555766629.763387405
995664.119693489766923.332903397995653.220345884767197.414063066
995724.150441759767388.232085081995999.539141817767527.529858928
996025.788614781767705.842776329996264.520191816767736.820943765
996202.864706069767830.279380338996491.460277964768126.343974079
996477.362844702768434.857833618 996335.85078025768657.830518711
996358.863206592769032.085241873996240.331275047769334.839252242
996356.440845923769483.855506402996266.937180571769501.402835264
996219.537654443769690.739360528996388.385872301769885.353532012
996377.030911598770135.470526011996461.813534969770423.731445473

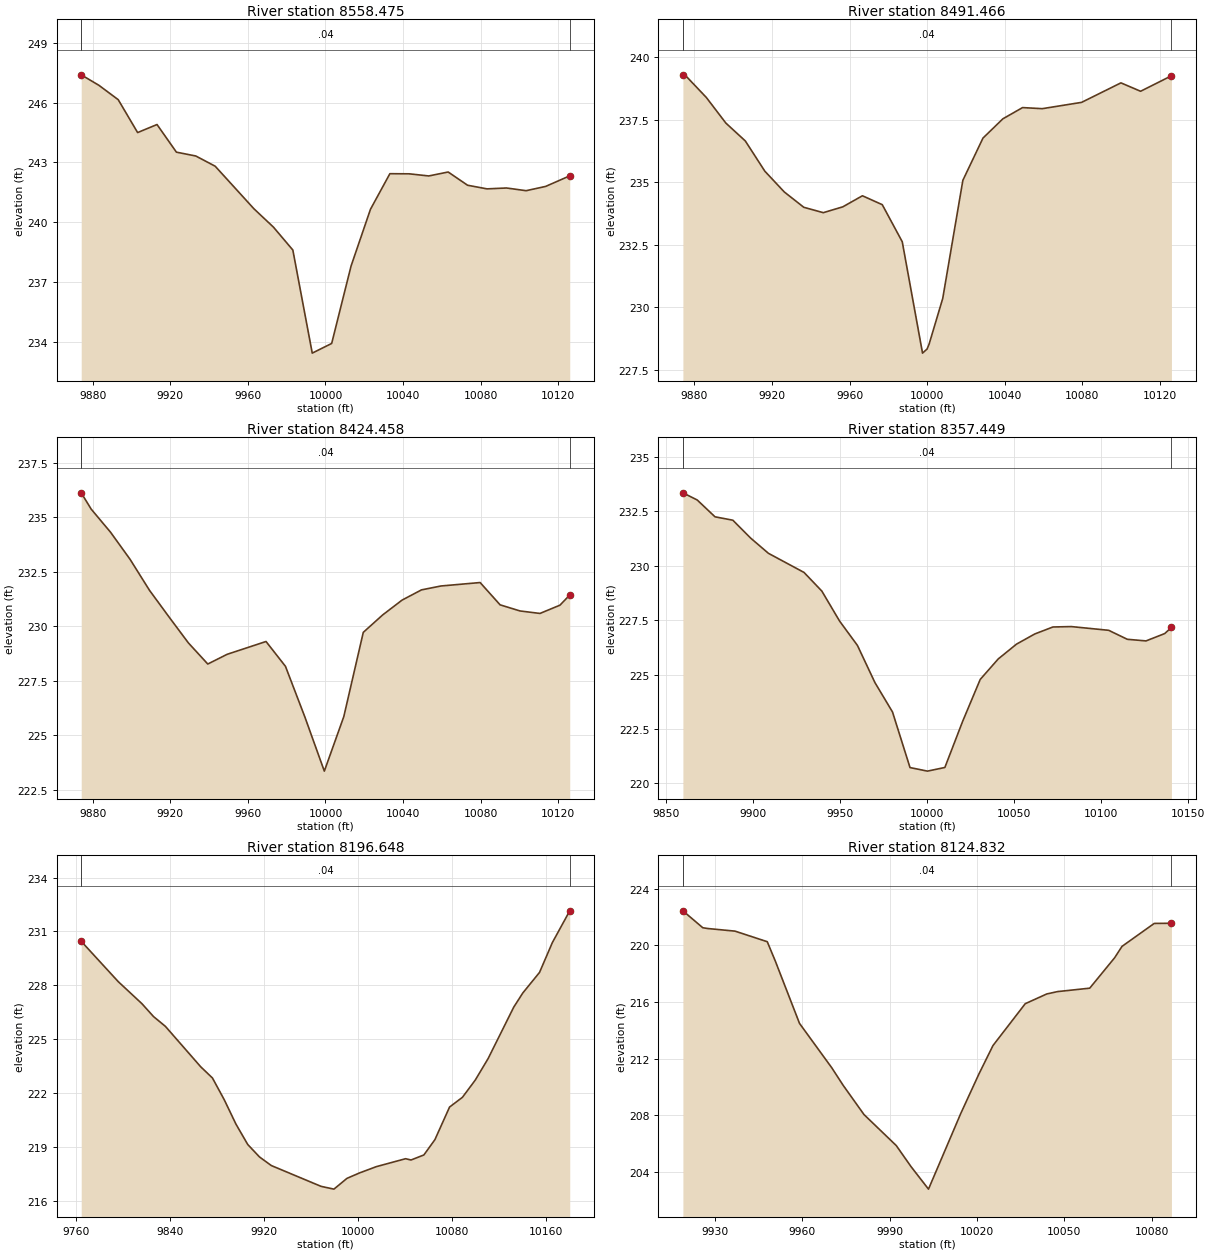
Type RM Length L Ch R = 1 ,8558.475,67.008500,67.008500,67.008500
XS GIS Cut Line= 6
995825.917958353763329.085650943995906.328459857763327.299963802
995952.811971878 763329.72347871995989.612604781763331.006094048
996031.653506245763328.378977935996077.351080178 763322.92780909
#Sta/Elev= 25
9874.021247.39519883.106246.87269893.108246.14959903.111244.50049913.113244.9034
9923.116243.51859933.118 243.3269943.121242.81289963.134240.67589973.147239.7614
 9983.16238.61179993.172233.443310003.19233.9287 10013.2237.8125 10023.2240.6546
10033.21242.438310043.22 242.43210053.24 242.32510063.26242.523510073.28241.8596
10083.32241.677910093.39241.721710103.46241.586410113.53241.800110125.97242.3308
#Mann= 3 , 0 , 0
9874.021    0.04       09874.021    0.04       010125.97    0.04       0
#XS Ineff= 2 , 0
       0                               0
Bank Sta=9874.021,10125.97
Exp/Cntr=0.3,0.1

Type RM Length L Ch R = 1 ,8491.466,67.008500,67.008500,67.008500
XS GIS Cut Line= 6
995832.959299483763413.079755506995920.657635211763404.352839383
995941.391616977763399.888819994995958.219991838763394.664766567
995990.479010284763385.745820773996080.672620212763370.334645996
#Sta/Elev= 26
9874.038 239.3029876.089239.21529886.138238.39439896.188237.37199906.237236.6559
9916.286235.44839926.336 234.6169936.385234.00379946.434233.78889956.484234.0218
9966.611234.4646 9976.84 234.1099987.153232.62599997.612228.17119999.962228.3356
   10001228.532610008.03230.358510018.41235.082910028.78236.771710039.06237.5435
 10049.2237.991710059.35237.948410079.64238.200710099.93238.980210110.07238.6444
10125.97239.2636
#Mann= 3 , 0 , 0
9874.038    0.04       09874.038    0.04       010125.97    0.04       0
#XS Ineff= 2 , 0
       0                               0
Bank Sta=9874.038,10125.97
Exp/Cntr=0.3,0.1

Type RM Length L Ch R = 1 ,8424.458,67.008500,67.008500,67.008500
XS GIS Cut Line= 6
995839.886900296763462.070499022995920.319876114763457.504911063
995987.306102065763462.448787299996011.077226403763462.506590519
996045.192681696 763458.32175272996089.917944458763447.527674146
#Sta/Elev= 25
9874.034236.12369879.164235.37789889.197234.3129 9899.23233.07449909.263231.6514
9919.285230.4359 9929.29229.24349939.295228.27439949.299  228.729969.334229.3068
9979.356228.16869989.377225.8428  9999.4223.363410009.44225.863110019.48229.7253
10029.49230.525510039.49231.205110049.52231.674510059.59231.852310079.74232.0102
10090.03230.988110100.31230.7075 10110.6230.593410120.89230.972310125.95231.4365
#Mann= 3 , 0 , 0
9874.034    0.04       09874.034    0.04       010125.95    0.04       0
#XS Ineff= 2 , 0
       0                               0
Bank Sta=9874.034,10125.95
Exp/Cntr=0.3,0.1

Type RM Length L Ch R = 1 ,8357.449,160.801100,160.801100,160.801100
XS GIS Cut Line= 6
995816.951736128 763550.78844512995915.108911244763529.669708759
995964.636424057763526.761554246995988.907088996763522.423138097
996031.876495339763509.022991609 996088.60866262763486.882952302
#Sta/Elev= 27
9859.619 233.3469867.852 233.0169878.081232.24329888.309232.08899898.538231.2674
9908.767230.56739929.225229.68899939.454 228.8339949.682227.45219959.911226.3369
 9969.99224.62599980.067 223.2799990.126220.725510000.15220.561810010.16220.7297
10020.32222.838610030.48224.774710040.83 225.71510051.31226.394510061.78226.8608
10072.26227.183210082.81227.201510104.28227.030610115.02226.617310125.75226.5432
10136.49226.880810140.36227.1603
#Mann= 3 , 0 , 0
9859.619    0.04       09859.619    0.04       010140.36    0.04       0
#XS Ineff= 2 , 0
       0                               0
Bank Sta=9859.619,10140.36
Exp/Cntr=0.3,0.1

Type RM Length L Ch R = 1 ,8196.648,71.815800,71.815800,71.815800
XS GIS Cut Line= 3
995833.514471382763659.762866676 996010.04692331763664.770879492
996228.521482617763568.992634311
#Sta/Elev= 30
9764.735230.45359796.233228.20669816.241 226.9879826.245226.26079836.249225.7219
9866.261223.47159876.265222.84539886.269221.63749896.273220.27439906.277219.1433
9916.281218.44959926.285217.97369968.584 216.8159979.503216.6616 9990.58217.2607
10001.34217.565610015.49217.911710040.39 218.35410045.02218.283610055.93218.5631
 10065.3219.414410077.77221.229910088.69221.770810099.61222.731210110.53223.9284
10132.37226.797410140.02227.5793 10154.2228.720810165.12230.382510179.89232.1491
#Mann= 3 , 0 , 0
9764.735    0.04       09764.735    0.04       010179.89    0.04       0
#XS Ineff= 2 , 0
       0                               0
Bank Sta=9764.735,10179.89
Exp/Cntr=0.3,0.1

Type RM Length L Ch R = 1 ,8124.832,73.315600,73.315600,73.315600
XS GIS Cut Line= 2
996038.842997044763728.623042956996190.335384905763656.632858664
#Sta/Elev= 24
9919.034222.4505 9925.85221.25549927.475221.20039936.922221.01389947.994220.2656
9950.773 218.8899959.065214.48649970.137211.34679974.072210.09829981.209208.0351
9992.281205.84219997.371204.347110003.35202.758910014.42208.107610020.67210.9075
 10025.5212.921110036.57215.879410043.97216.569410047.64216.734710058.71216.9781
10067.27219.132510069.78219.933610080.85221.559110086.76  221.57
#Mann= 3 , 0 , 0
9919.034    0.04       09919.034    0.04       010086.76    0.04       0
#XS Ineff= 2 , 0
       0                               0
Bank Sta=9919.034,10086.76
Exp/Cntr=0.3,0.1

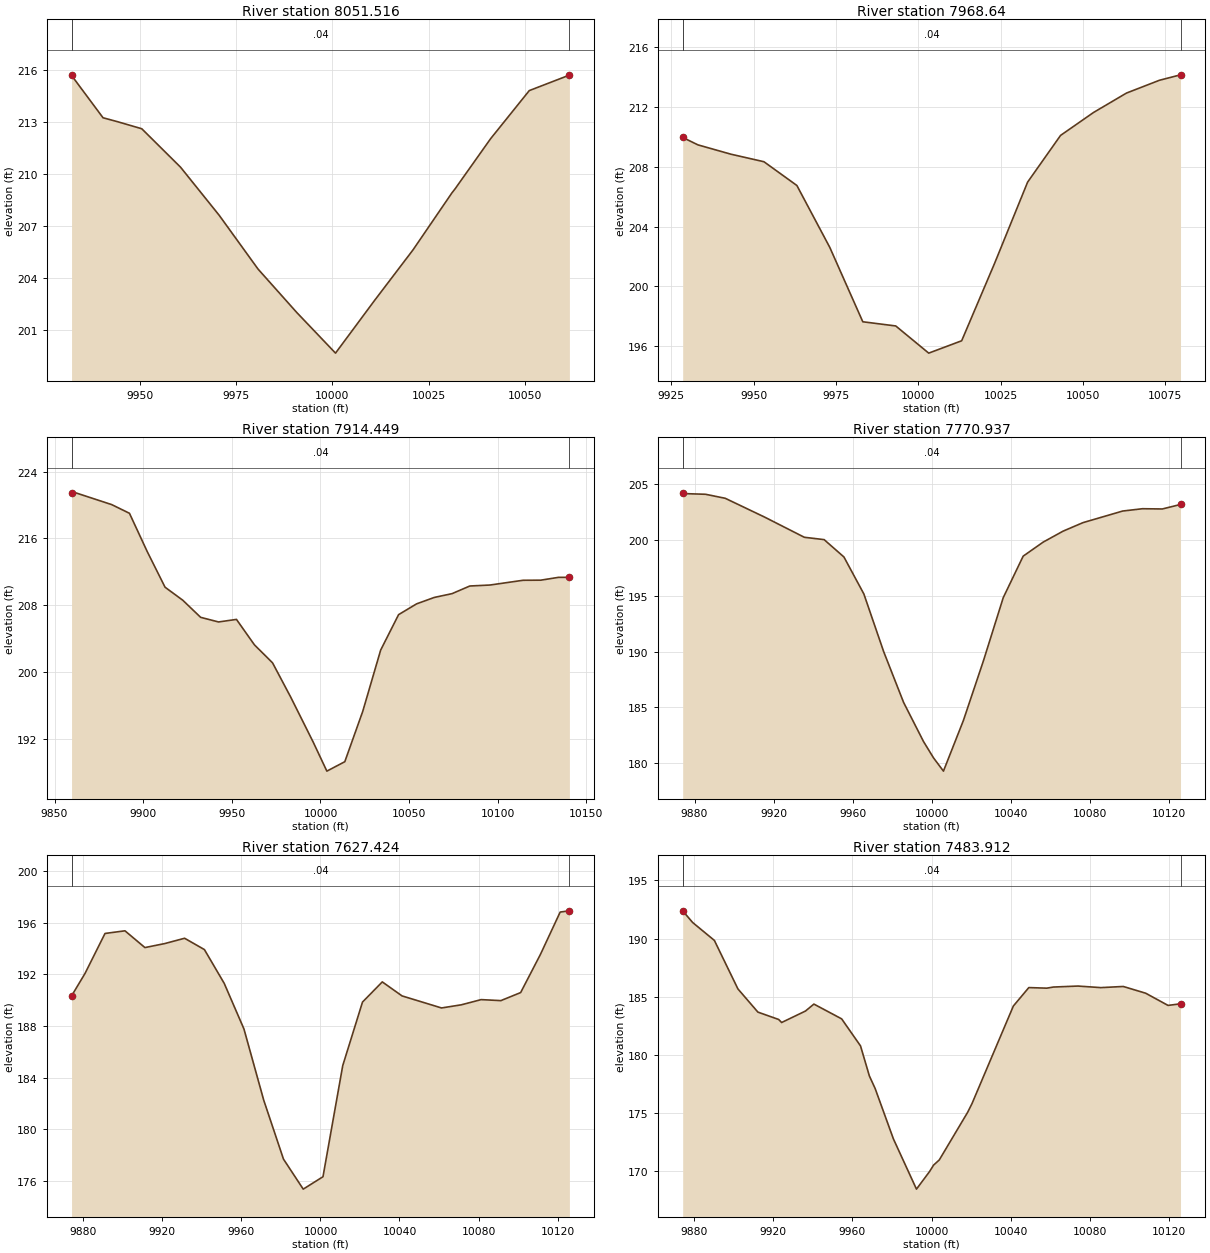
Type RM Length L Ch R = 1 ,8051.516,82.877000,82.877000,82.877000
XS GIS Cut Line= 2
996076.880114287763766.368584648996205.352336526763751.611640215
#Sta/Elev= 17
9932.235 215.6759940.408213.23829944.228213.00839950.474 212.6059960.539210.3933
9970.605207.61639980.671204.52729990.737202.0243 10000.8199.685910010.87202.6974
10020.93205.6306   10031208.899410031.86209.145710041.07212.027410051.13214.8019
 10061.2215.663310061.55215.7098
#Mann= 3 , 0 , 0
9932.235    0.04       09932.235    0.04       010061.55    0.04       0
#XS Ineff= 2 , 0
       0                               0
Bank Sta=9932.235,10061.55
Exp/Cntr=0.3,0.1

Type RM Length L Ch R = 1 , 7968.64,54.190500,54.190500,54.190500
XS GIS Cut Line= 2
996080.352336526 763843.62552911996231.394003212763837.549140215
#Sta/Elev= 17
9928.484209.94629933.135 209.4519943.143208.82919953.151208.32779963.159206.7417
9973.167 202.6039983.175197.64479993.183197.365110003.19195.5519 10013.2196.3777
10023.21201.553810033.22206.965910043.22210.082210053.23211.613810063.24212.9101
10073.25213.764210079.65214.1275
#Mann= 3 , 0 , 0
9928.484    0.04       09928.484    0.04       010079.65    0.04       0
#XS Ineff= 2 , 0
       0                               0
Bank Sta=9928.484,10079.65
Exp/Cntr=0.3,0.1

Type RM Length L Ch R = 1 ,7914.449,143.512300,143.512300,143.512300
XS GIS Cut Line= 6
996012.342891238763878.638251353996046.645070487763879.321066071
996086.345834489763882.630923822996205.291352144763902.995231447
996246.345837167763905.522782118996291.135825932763905.382956581
#Sta/Elev= 28
9859.595221.47029862.253221.44879882.257220.05649892.259219.01629902.288214.4194
9912.323210.15279922.357208.58419932.392206.54089942.497205.98379952.613206.2891
9962.736203.24329972.979201.07619983.221196.96689995.909191.5675 10003.6188.0939
10013.72 189.22410023.83195.254410033.95202.608710044.06 206.86110054.18208.1504
 10064.2208.924510074.22  209.3810084.24210.295310095.61210.412210114.26 210.982
10124.26210.994810134.26211.3336 10140.4211.3341
#Mann= 3 , 0 , 0
9859.595    0.04       09859.595    0.04       0 10140.4    0.04       0
#XS Ineff= 2 , 0
       0                               0
Bank Sta=9859.595,10140.4
Exp/Cntr=0.3,0.1

Type RM Length L Ch R = 1 ,7770.937,143.512400,143.512400,143.512400
XS GIS Cut Line= 6
995993.474288729764041.068614893996032.165480695764040.611862225
996074.085669161764037.865095534996118.067321885764032.713959441
996190.374237689764022.975300219996244.146986921764017.666127932
#Sta/Elev= 25
9874.014204.2377 9875.54204.1632 9885.54204.10829895.541 203.7499915.548202.0567
9935.591200.25439945.613200.04389955.638198.48679965.707195.17969975.775189.9913
9985.843185.45099995.912181.9512   10001180.4797   10006179.297910016.09183.8329
10026.18189.150210036.27194.844810046.36198.562910056.45199.817410066.54200.8015
10076.61201.564310096.71202.605210106.75202.8128 10116.8202.7907   10126203.1954
#Mann= 3 , 0 , 0
9874.014    0.04       09874.014    0.04       0   10126    0.04       0
#XS Ineff= 2 , 0
       0                               0
Bank Sta=9874.014,10126
Exp/Cntr=0.3,0.1

Type RM Length L Ch R = 1 ,7627.424,143.512300,143.512300,143.512300
XS GIS Cut Line= 6
996048.242951783764155.357874238996085.977714792764160.795203747
996118.792565378764163.481291873996172.719383759764163.542076704
996225.567690747764162.962664014996299.653379383764165.652088153
#Sta/Elev= 26
9874.024190.32659880.851192.07229890.954195.16099901.057 195.3669911.161194.0692
9921.201194.37929931.234194.79029941.268193.91399951.281191.30449961.281187.7718
9971.281182.26819981.281177.70759991.281175.384510001.28176.343610011.28184.9401
10021.28189.853510031.29191.414510041.29190.330410061.29189.3983 10071.3189.6419
10081.31190.043110091.31189.966310101.32190.588310111.33  193.5410121.33196.8166
10125.99196.9118
#Mann= 3 , 0 , 0
9874.024    0.04       09874.024    0.04       010125.99    0.04       0
#XS Ineff= 2 , 0
       0                               0
Bank Sta=9874.024,10125.99
Exp/Cntr=0.3,0.1

Type RM Length L Ch R = 1 ,7483.912,143.512300,143.512300,143.512300
XS GIS Cut Line= 6
996000.437601319764193.361930204996058.096568784764224.608801839
996080.166518466764247.054723627996103.505866231764287.517213558
996118.786303439764305.080590071996190.560141637764349.071930126
#Sta/Elev= 30
9874.189192.39079879.208191.38929890.209189.84559902.109185.67599912.212183.6788
9922.702183.04689924.214182.78479936.248183.77039940.523184.36879954.547183.0981
9964.084180.77359968.572178.18489971.453177.11739980.714 172.7729992.369168.4535
    9999 169.969   10001170.516310003.89170.962510018.17175.040710020.45175.8147
10041.35184.203310049.16185.788410058.23 185.73910061.56185.834710073.96  185.92
10085.58185.785710096.91185.884210108.23185.305310119.55184.255110125.85184.3943
#Mann= 3 , 0 , 0
9874.189    0.04       09874.189    0.04       010125.85    0.04       0
#XS Ineff= 2 , 0
       0                               0
Bank Sta=9874.189,10125.85
Exp/Cntr=0.3,0.1

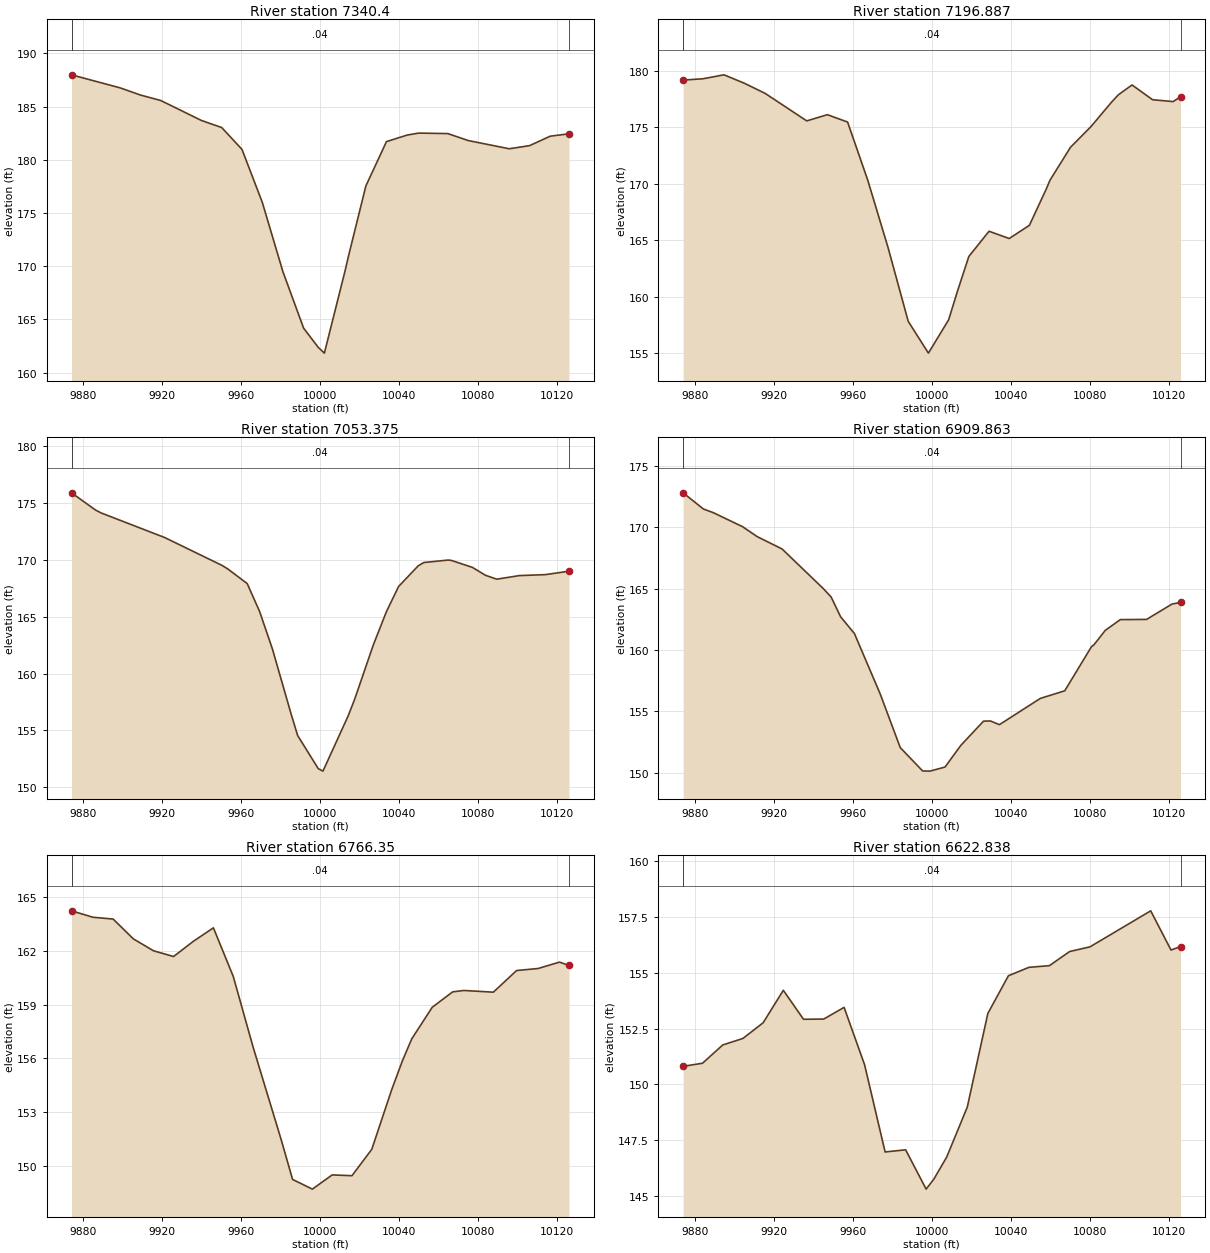
Type RM Length L Ch R = 1 ,  7340.4,143.512400,143.512400,143.512400
XS GIS Cut Line= 6
995931.051937412764369.224874252996025.661679113764392.011137178
 996052.07537335764400.266614079 996053.96414065764400.924305562
996080.297663312764409.440580602996174.179407703764435.067712459
#Sta/Elev= 24
9874.011187.97479898.644186.7493 9908.93186.07659919.216185.56299939.788183.6906
9950.074183.0257 9960.36180.97259970.646176.0005 9981.11169.48019991.587 164.182
    9999162.384310002.09161.8413 10012.6169.584110014.25170.906310023.11177.5373
10033.55181.701610043.92182.312710049.79182.502910064.65182.456710075.01181.8005
10095.75181.031810106.11181.328310116.48182.210510125.99182.4376
#Mann= 3 , 0 , 0
9874.011    0.04       09874.011    0.04       010125.99    0.04       0
#XS Ineff= 2 , 0
       0                               0
Bank Sta=9874.011,10125.99
Exp/Cntr=0.3,0.1

Type RM Length L Ch R = 1 ,7196.887,143.512300,143.512300,143.512300
XS GIS Cut Line= 6
995915.461514063  764508.5902928995983.004201736764530.571817574
996035.706013359764541.994256224996037.638875921764542.508106704
996084.713447034764552.576723521996158.618527595764573.616935355
#Sta/Elev= 28
9874.045179.18979884.076179.30659894.757179.65629905.108178.90639915.625178.0083
9936.657175.57569947.117176.12549957.349175.47279967.581170.31199977.813164.3721
9988.045157.82759998.278155.004710008.53157.959110012.91160.442410018.75163.5672
10028.98 165.80110039.21165.156710049.44166.328310057.99169.547210059.83170.3124
10070.23173.234710080.63175.074810091.03177.236410094.51177.891510101.42178.7588
10111.82177.449110122.22177.287210125.98177.7079
#Mann= 3 , 0 , 0
9874.045    0.04       09874.045    0.04       010125.98    0.04       0
#XS Ineff= 2 , 0
       0                               0
Bank Sta=9874.045,10125.98
Exp/Cntr=0.3,0.1

Type RM Length L Ch R = 1 ,7053.375,143.512300,143.512300,143.512300
XS GIS Cut Line= 5
995865.396882069764585.633913358 995963.15340291764663.501821319
995964.706645519764664.761756792996006.786202032764698.196469696
996064.777175455764739.566825516
#Sta/Elev= 28
9874.021175.89769886.298174.37089889.054174.12659921.154171.97059950.222169.5199
9953.254169.19499963.007167.91799969.304165.45619975.791162.16029985.354156.3857
9988.576154.5537    9999151.644510001.37151.426910014.15156.285610017.46157.7596
10026.92162.540910033.53165.450710039.69167.660810049.61169.476310052.46169.7678
10064.84169.987110066.46169.952810077.12169.338810083.68168.6489 10089.4168.3045
 10100.9168.621610113.97168.703410125.98 169.005
#Mann= 3 , 0 , 0
9874.021    0.04       09874.021    0.04       010125.98    0.04       0
#XS Ineff= 2 , 0
       0                               0
Bank Sta=9874.021,10125.98
Exp/Cntr=0.3,0.1

Type RM Length L Ch R = 1 ,6909.863,143.512400,143.512400,143.512400
XS GIS Cut Line= 6
  995784.6196852764657.458621422995811.311538654764686.448252472
995830.420412045764711.751849013995886.656670251764805.887977629
995908.851195754764830.175583288995938.305449734764854.345603814
#Sta/Elev= 28
9874.038172.79619884.289 171.4829889.363171.17849904.126170.04279911.476169.2375
9924.161168.22499945.153164.98099948.987164.31579953.773162.7103 9960.79161.3405
9973.839156.42499983.982152.0619 9995.32150.1585    9999150.144910006.66150.4772
10014.73152.253610026.16154.212710029.65154.227610034.21153.926310054.92156.0645
10067.29156.683710080.81160.270210082.11160.432610087.82161.603110095.42162.4768
10108.71162.492510121.64163.745710125.92163.8736
#Mann= 3 , 0 , 0
9874.038    0.04       09874.038    0.04       010125.92    0.04       0
#XS Ineff= 2 , 0
       0                               0
Bank Sta=9874.038,10125.92
Exp/Cntr=0.3,0.1

Type RM Length L Ch R = 1 , 6766.35,143.512300,143.512300,143.512300
XS GIS Cut Line= 6
 995644.41207917 764837.69629309995721.362366431764851.600193512
995790.723842348764849.323579382995810.370090502764850.870761406
  995840.4871948764859.115472903995889.362179757764880.096779628
#Sta/Elev= 27
 9874.04164.22499884.874163.86659895.107163.76649905.339162.66199915.571161.9973
9925.708161.67829935.795162.53189945.883163.2767 9955.94160.56679965.943156.6448
 9980.16151.48789985.964149.25749995.991148.716910006.02149.509610016.05149.4648
10026.07150.934710036.11154.242210041.49155.842910046.29157.086710056.66158.8467
10067.03159.709910072.72159.786710087.64159.691910099.39160.897810110.28161.0113
10121.16 161.36710125.91161.1797
#Mann= 3 , 0 , 0
 9874.04    0.04       0 9874.04    0.04       010125.91    0.04       0
#XS Ineff= 2 , 0
       0                               0
Bank Sta=9874.04,10125.91
Exp/Cntr=0.3,0.1

Type RM Length L Ch R = 1 ,6622.838,143.512300,143.512300,143.512300
XS GIS Cut Line= 6
995645.389698252764962.893203997995719.657639019764978.960878483
995766.810769417764992.286409063995768.727883075764992.856211856
995820.501544716765007.977651761995889.711107445765024.038615843
#Sta/Elev= 25
9874.014150.81189883.847 150.9519894.078151.76939904.309152.06129914.541152.7622
9924.772154.21689935.003152.91959945.235152.92889955.552153.45279965.943150.8812
9976.335146.97769986.727147.07339997.118145.3127   10001145.756810007.53146.7481
10017.95 148.98310028.37153.179610038.79154.868310049.21155.246110059.55155.3197
10069.82155.953610080.09156.161610110.88157.776110121.15156.021510125.99156.1721
#Mann= 3 , 0 , 0
9874.014    0.04       09874.014    0.04       010125.99    0.04       0
#XS Ineff= 2 , 0
       0                               0
Bank Sta=9874.014,10125.99
Exp/Cntr=0.3,0.1

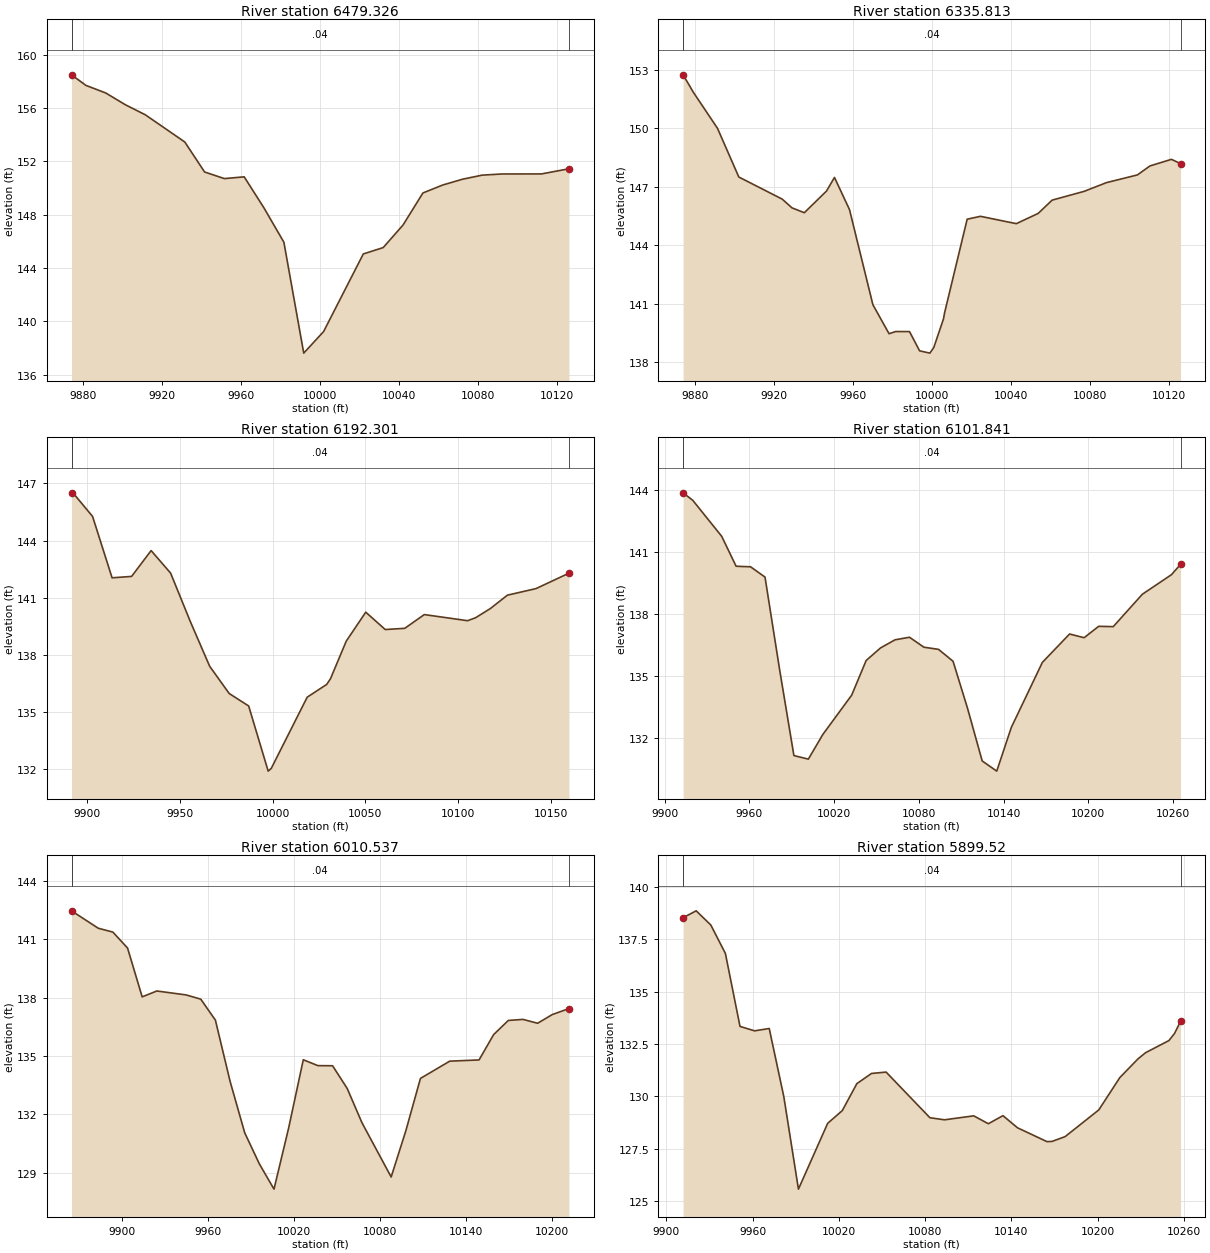
Type RM Length L Ch R = 1 ,6479.326,143.512400,143.512400,143.512400
XS GIS Cut Line= 6
995587.745450368765115.495725462995665.604010095765120.333261532
995712.332993702765125.205940088995714.326085218765125.039849128
995773.283135693765131.596872127995838.915947024765132.468849641
#Sta/Elev= 23
9874.009158.47869881.277157.68729891.297157.11969901.316156.23089911.335155.4843
9931.374153.44149941.393 151.1939951.412 150.6959961.465150.82729971.519148.4879
9981.573 145.9229991.627137.605210001.68139.2221 10021.8145.044310031.86145.5201
10041.92147.212110051.99149.616610062.04150.214310072.04150.648510082.04150.9551
10092.04151.041610112.04151.046410125.96151.4315
#Mann= 3 , 0 , 0
9874.009    0.04       09874.009    0.04       010125.96    0.04       0
#XS Ineff= 2 , 0
       0                               0
Bank Sta=9874.009,10125.96
Exp/Cntr=0.3,0.1

Type RM Length L Ch R = 1 ,6335.813,143.512300,143.512300,143.512300
XS GIS Cut Line= 6
995648.889316906765316.975404029995685.391855554765302.062573716
 995714.01351344765287.665030715995815.355236212765222.067913092
995842.144983323  765207.9493602 995869.25944333 765196.49999472
#Sta/Elev= 30
9874.025152.73299879.249151.83219891.429149.99489902.231147.49889924.212146.3661
9929.173145.91869935.406  145.679946.645146.77969950.682147.47769958.302145.8261
9970.143140.9565 9978.32139.47399981.729 139.5849988.694139.58059993.788138.5964
    9999138.4781   10001138.770510005.91140.236610006.47140.550810017.89 145.338
10024.62145.485710042.77145.109510053.84145.632510060.93146.314810077.15146.7647
10088.45147.211610104.11147.606310110.48148.066910121.34148.403910125.96148.1851
#Mann= 3 , 0 , 0
9874.025    0.04       09874.025    0.04       010125.96    0.04       0
#XS Ineff= 2 , 0
       0                               0
Bank Sta=9874.025,10125.96
Exp/Cntr=0.3,0.1

Type RM Length L Ch R = 1 ,6192.301,90.459700,90.459700,90.459700
XS GIS Cut Line= 3
995734.215183765765408.729695767 995921.93219763765346.880737439
995979.440878212765305.648098558
#Sta/Elev= 27
9891.461146.50469892.287146.49569902.816145.26689913.344142.04729923.873142.1204
9934.402143.47559944.931142.2935 9955.46139.77599965.988137.41029976.517135.9804
9987.046135.32499997.575131.90789999.247132.054310018.63135.786610029.16 136.456
 10031.2136.754710039.69138.724510050.22140.244610060.75139.334110071.28139.3974
10081.81140.118810105.18139.797710109.49139.953310117.49140.436610126.66 141.137
 10142.1141.481410159.87142.2906
#Mann= 3 , 0 , 0
9891.461    0.04       09891.461    0.04       010159.87    0.04       0
#XS Ineff= 2 , 0
       0                10058.53       0
Bank Sta=9891.461,10159.87
Exp/Cntr=0.3,0.1

Type RM Length L Ch R = 1 ,6101.841,91.304400,91.304400,91.304400
XS GIS Cut Line= 3
995748.321086496765481.429348543995914.336711526765445.622056872
996091.203030974765401.134209648
#Sta/Elev= 30
9913.049143.84439919.882143.48169940.342141.74149950.572140.29029960.802140.2633
9971.031139.76589981.261135.33259991.491131.126110001.72130.953310011.95 132.145
10032.41134.051510042.64135.726310052.87136.3383 10063.1136.729410073.33136.8528
10083.57136.370910093.88136.268210104.19135.6901 10114.5133.399510124.81130.8666
10135.12130.372910145.44132.489210167.42135.635510186.68137.010510196.99136.8307
 10207.3137.382510217.62137.367310238.24138.936310258.86139.883210265.26140.3819
#Mann= 3 , 0 , 0
9913.049    0.04       09913.049    0.04       010265.26    0.04       0
#XS Ineff= 2 , 0
       0                10089.34       0
Bank Sta=9913.049,10265.26
Exp/Cntr=0.3,0.1

Type RM Length L Ch R = 1 ,6010.537,111.016900,111.016900,111.016900
XS GIS Cut Line= 2
995766.767267048765547.618584663996106.394003212765476.004001305
#Sta/Elev= 30
9864.585 142.4539883.219141.55949893.439141.36089903.659140.54499913.878138.0363
9924.098138.33779944.538 138.1369954.758137.91859964.978136.84259975.198133.7072
9985.418131.06049995.638129.464810005.86 128.16710016.08131.3026 10026.3134.8075
10036.52134.505910046.74134.499910056.96133.333110067.18131.584510087.62128.7896
10097.84131.157810108.06133.8499 10128.5134.736610148.94134.798310159.16136.1015
10169.38136.8256 10179.6136.879910189.82136.681410200.04137.127510211.68137.4342
#Mann= 3 , 0 , 0
9864.585    0.04       09864.585    0.04       010211.68    0.04       0
#XS Ineff= 2 , 0
       0                 10036.8       0
Bank Sta=9864.585,10211.68
Exp/Cntr=0.3,0.1

Type RM Length L Ch R = 1 , 5899.52,120.204100,120.204100,120.204100
XS GIS Cut Line= 3
995796.064142048765643.104695767996044.545044839 765597.53177911
996118.329767078765540.023098528
#Sta/Elev= 30
9911.614138.53689920.699138.86489930.866138.18899941.032136.83079951.199133.3448
9961.366133.13269971.533 133.245  9981.7129.98599991.866125.5735 10012.2 128.715
10022.37129.322310032.53130.6119 10042.7131.096810052.87 131.16410083.37128.9834
10093.53128.884310113.87129.073510124.03128.6961 10134.2129.081810144.37128.5011
10164.82127.842610168.36127.851710177.49128.082510200.89129.356210215.53130.9006
10228.21131.795910233.43132.088310249.69132.668110253.57133.003210257.79133.5886
#Mann= 3 , 0 , 0
9911.614    0.04       09911.614    0.04       010257.79    0.04       0
#XS Ineff= 2 , 0
       0                10052.34       0
Bank Sta=9911.614,10257.79
Exp/Cntr=0.3,0.1

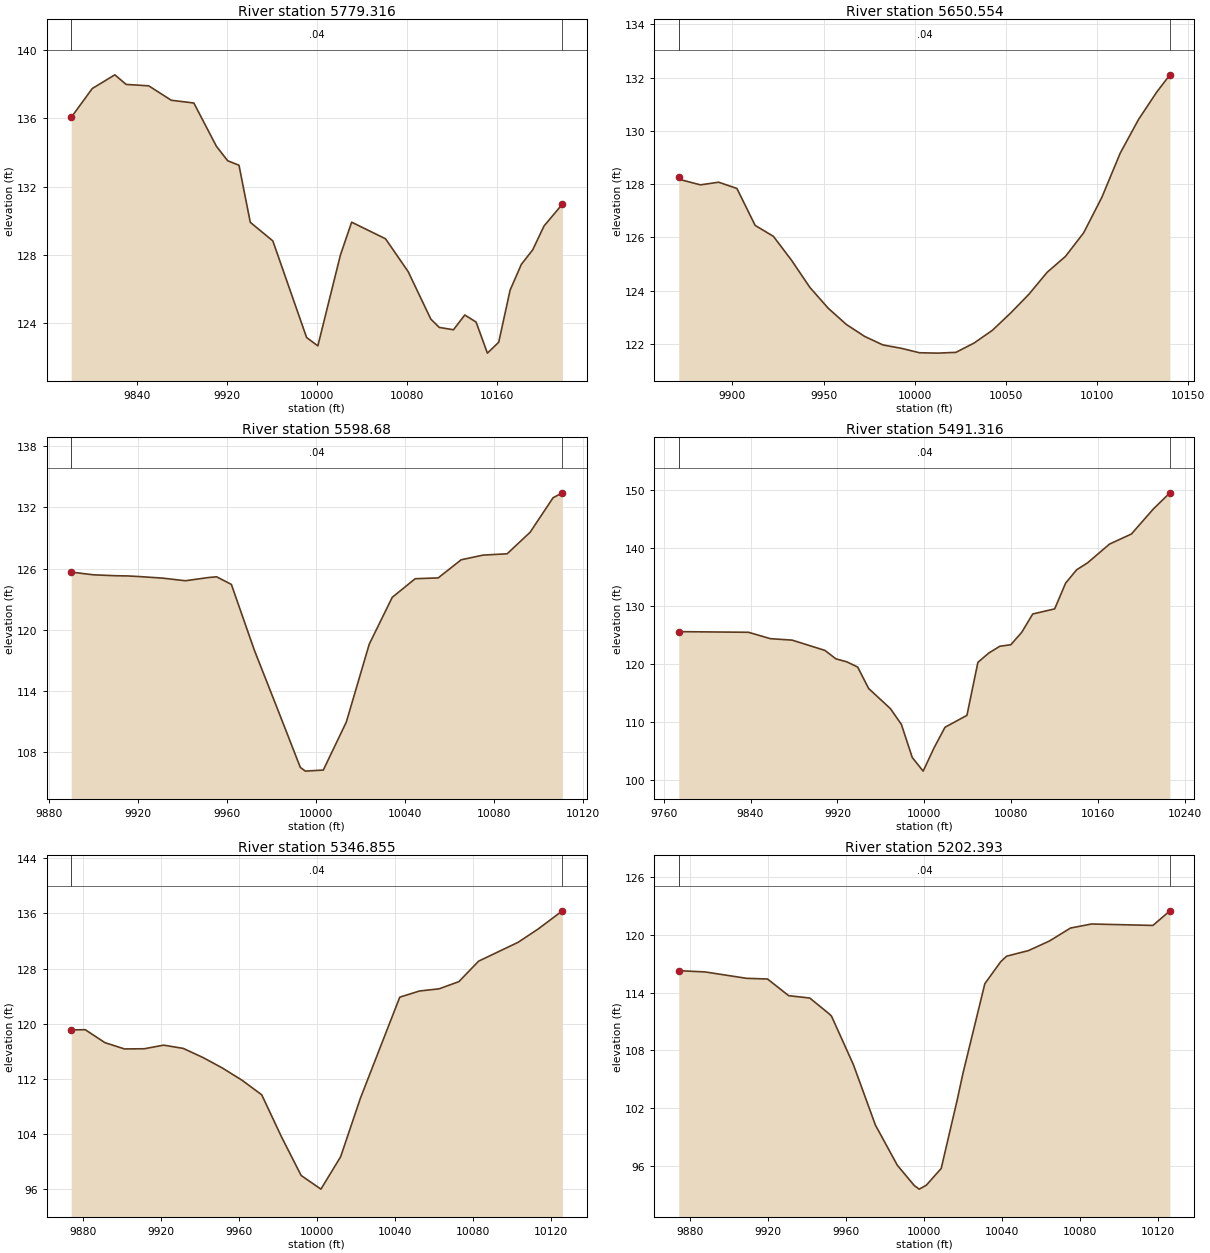
Type RM Length L Ch R = 1 ,5779.316,128.762200,128.762200,128.762200
XS GIS Cut Line= 6
995686.345086229765755.822619665995858.514518423765743.435995208
995903.079409589765742.942785514995905.079066742765742.979816202
995945.579392469 765742.09057893996121.253633838765723.454747258
#Sta/Elev= 30
9781.818136.05489800.521137.74419820.573138.54489830.599137.9846 9850.65137.9011
9870.702137.05729890.754136.89599910.805134.36239920.831133.51799930.857133.2572
9940.883129.91649960.918128.8298 9990.92123.177410000.92122.688610020.93 127.996
10030.93129.925110061.04128.953210081.15127.031810101.26124.256810108.73123.7693
10121.38123.630110131.43124.495410141.49124.083310151.54122.2642 10161.6 122.902
10171.66125.942810181.71127.460710191.77 128.30610201.83129.702310218.17130.9805
#Mann= 3 , 0 , 0
9781.818    0.04       09781.818    0.04       010218.17    0.04       0
#XS Ineff= 2 , 0
       0                10049.41       0
Bank Sta=9781.818,10218.17
Exp/Cntr=0.3,0.1

Type RM Length L Ch R = 1 ,5650.554,51.873700,51.873700,51.873700
XS GIS Cut Line= 2
995813.131859243765855.834915295996082.229081422765868.855748624
#Sta/Elev= 30
9870.557128.27459872.428128.15039882.439127.97129892.451128.07049902.463127.8359
9912.474126.44849922.486126.03789932.498125.1324 9942.51124.11789952.521123.3392
9962.533122.72619972.545122.27859982.556121.95899992.568121.834310002.58121.6658
10012.59121.6515 10022.6121.680410032.61122.033310042.63122.510810052.64123.1613
10060.19123.690710062.65123.865210072.66124.689810082.67125.283210092.69126.1746
 10102.7127.512810112.71129.162610122.72130.423310132.73131.455910139.97132.1034
#Mann= 3 , 0 , 0
9870.557    0.04       09870.557    0.04       010139.97    0.04       0
#XS Ineff= 2 , 0
       0                 10033.9       0
Bank Sta=9870.557,10139.97
Exp/Cntr=0.3,0.1

Type RM Length L Ch R = 1 , 5598.68,107.364100,107.364100,107.364100
XS GIS Cut Line= 2
995815.301998138765878.621373639996029.060678661765933.959915295
#Sta/Elev= 28
9890.008125.64779900.025125.38219910.355125.28899915.459125.27229920.685125.2091
9931.014125.05929941.344124.80059951.674125.1149 9955.36125.18629962.003 124.441
9972.333117.98439982.663112.26239992.992 106.4849995.261106.116410003.32 106.223
10013.65110.922810023.98118.578510034.31123.171810035.16 123.32310044.64124.9999
10054.97125.0803 10065.3126.857210075.06127.312510075.63127.322210085.96127.4459
10096.29129.558110106.62132.948210110.81133.4284
#Mann= 3 , 0 , 0
9890.008    0.04       09890.008    0.04       010110.81    0.04       0
#XS Ineff= 2 , 0
       0                10077.95       0
Bank Sta=9890.008,10110.81
Exp/Cntr=0.3,0.1

Type RM Length L Ch R = 1 ,5491.316,144.461300,144.461300,144.461300
XS GIS Cut Line= 6
995641.105487246765973.522511806 995848.43607672765994.843005525
995865.088653919765995.817952571995867.083914576765995.680348387
995876.755165092765996.294288243996090.090201971766026.099186905
#Sta/Elev= 30
9773.895125.57819838.126 125.4689858.232124.37189878.337124.11739908.496122.3524
9918.548120.90489928.601120.39249938.654119.48869948.707115.81289968.812112.3396
9978.865109.64269988.894103.94589998.911101.605710008.93105.603710019.02109.1419
10039.21111.189810049.31120.3021 10059.4121.9089 10069.5123.0679 10079.6123.3269
 10089.7125.471210099.79128.610610119.99129.488810130.08133.919610140.18136.2004
10150.28137.402310170.47140.623410190.67142.361510210.86146.6662 10226.1149.4345
#Mann= 3 , 0 , 0
9773.895    0.04       09773.895    0.04       0 10226.1    0.04       0
#XS Ineff= 2 , 0
       0                               0
Bank Sta=9773.895,10226.1
Exp/Cntr=0.3,0.1

Type RM Length L Ch R = 1 ,5346.855,144.461300,144.461300,144.461300
XS GIS Cut Line= 5
995767.825957547766120.233039811995871.422696338766131.410779225
995891.943745364766134.758572375995893.903046661766135.159992885
996017.535897037766153.531793188
#Sta/Elev= 24
 9874.01119.11319881.225119.14049891.283117.26959901.341116.35619911.399116.3805
9921.457116.90469931.516116.42959941.574115.11539951.632113.5809 9961.69111.8126
9971.748109.70649981.832103.64439991.96498.0211910002.1196.0438310012.22 100.736
10022.33109.194210042.55123.856110052.66124.748910062.77125.066710072.88126.1077
10082.99129.071310103.21131.798710113.32133.686310125.99136.3659
#Mann= 3 , 0 , 0
 9874.01    0.04       0 9874.01    0.04       010125.99    0.04       0
#XS Ineff= 2 , 0
       0                               0
Bank Sta=9874.01,10125.99
Exp/Cntr=0.3,0.1

Type RM Length L Ch R = 1 ,5202.393,144.461400,144.461400,144.461400
XS GIS Cut Line= 6
995722.258329943766216.580085544 995758.17281961766229.366523246
995788.510830029766242.165294629995886.350005858766292.063131974
 995916.97628668766304.152400941995953.303848321766315.704360508
#Sta/Elev= 26
9874.029116.26819887.554116.13959908.784 115.4759919.562115.40499930.415113.6747
9941.269113.42569951.258111.77429952.382111.54989963.637106.49999974.891100.2422
9986.14596.064029994.85393.954279997.39993.58338   1000193.9878810008.6595.73271
10016.86102.850710019.84105.637210031.03114.916910039.16117.199510042.21117.7746
 10053.4118.354510064.21119.355110074.96120.696310085.71121.117210117.24 120.968
10125.96122.4843
#Mann= 3 , 0 , 0
9874.029    0.04       09874.029    0.04       010125.96    0.04       0
#XS Ineff= 2 , 0
       0                               0
Bank Sta=9874.029,10125.96
Exp/Cntr=0.3,0.1

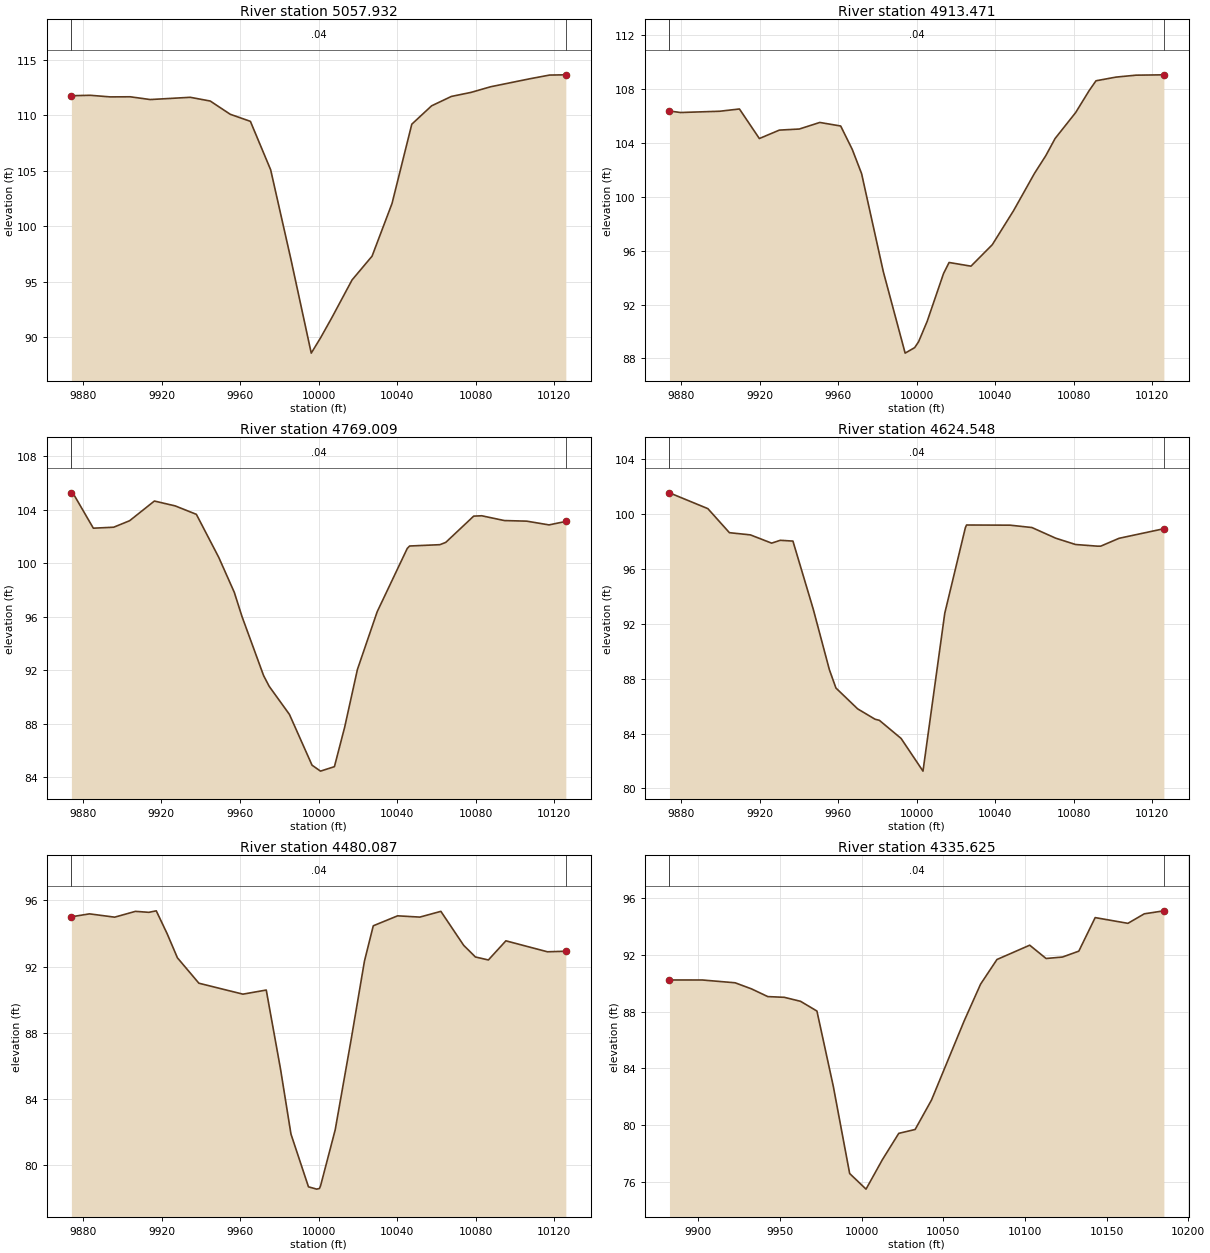
Type RM Length L Ch R = 1 ,5057.932,144.461300,144.461300,144.461300
XS GIS Cut Line= 6
995655.574211521766371.901628302995739.322206768766388.321266769
 995787.93739887766401.688827132995812.078384756766406.758049852
 995850.09868941766411.273486065995903.236380188766413.881514395
#Sta/Elev= 25
9874.031111.74419883.636111.78199893.827111.63859904.017 111.6489914.208111.3997
9934.588111.60099944.779111.26669954.969110.07429965.243109.4369 9975.58105.0707
9985.91797.000419996.25588.57155   1000189.9497910006.7491.7605310017.0395.15498
10027.2597.3032810037.42102.047410047.49109.181910057.56110.833110067.63111.6783
10077.68112.044310087.69 112.55210107.71113.272810117.72 113.60410125.97113.6251
#Mann= 3 , 0 , 0
9874.031    0.04       09874.031    0.04       010125.97    0.04       0
#XS Ineff= 2 , 0
       0                               0
Bank Sta=9874.031,10125.97
Exp/Cntr=0.3,0.1

Type RM Length L Ch R = 1 ,4913.471,144.461300,144.461300,144.461300
XS GIS Cut Line= 6
995699.367266657766560.196598564995737.443848107 766558.79904515
995769.743149895766552.578365046995870.101618951766508.242951309
995901.528588514766498.452856411995938.927709938766491.125638276
#Sta/Elev= 30
9874.093106.36699879.729106.25399899.743 106.3489909.749106.5164 9919.89104.3222
9930.074104.94779940.257105.02819950.683105.51639961.326105.25179967.219103.5143
 9971.97101.71979983.02194.44756 9994.1688.39004    999988.79754   1000189.23257
10005.3690.7426910013.6994.2906310016.5595.11944 10027.794.8465110038.55 96.4405
 10049.498.9705610060.06101.740110065.83103.054710070.53104.321510081.01106.2495
10087.85107.870310091.38  108.6110101.57108.882510111.76109.026810125.96109.0521
#Mann= 3 , 0 , 0
9874.093    0.04       09874.093    0.04       010125.96    0.04       0
#XS Ineff= 2 , 0
       0                               0
Bank Sta=9874.093,10125.96
Exp/Cntr=0.3,0.1

Type RM Length L Ch R = 1 ,4769.009,144.461300,144.461300,144.461300
XS GIS Cut Line= 6
995724.207655193766597.280283125995768.649270434766609.259598301
995803.230510461766625.735849565995818.804859922766640.593682574
995854.654339713766693.933583201 995922.52616048766737.907705467
#Sta/Elev= 30
9874.189105.25849875.009105.23259885.366102.61489895.723102.6879 9903.85103.1744
9916.437104.64489927.053104.28099937.819103.64959949.163100.44739957.10897.82474
9961.05396.006849972.02991.599959974.87490.795759985.19888.693079996.695 84.8995
   1000184.4546810008.0984.7882610013.3387.75369 10019.892.0548310029.8696.36799
10045.17101.101410046.36101.2824 10061.8101.382510064.77101.553910078.99103.5165
10083.07103.543610094.61103.185310105.97103.140910117.34102.860710125.89103.1212
#Mann= 3 , 0 , 0
9874.189    0.04       09874.189    0.04       010125.89    0.04       0
#XS Ineff= 2 , 0
       0                               0
Bank Sta=9874.189,10125.89
Exp/Cntr=0.3,0.1

Type RM Length L Ch R = 1 ,4624.548,144.461400,144.461400,144.461400
XS GIS Cut Line= 5
995626.938740888766713.222428629995694.538199197766741.460317942
995741.244826931766763.669568593995742.995982299766764.635723279
995855.556055931766818.982723188
#Sta/Elev= 26
9874.022101.55829893.595100.40559904.57798.65176 9915.2798.490849926.10897.88914
9930.521 98.09639936.94598.038539947.28293.084889955.525 88.65959958.86687.32197
9969.93985.801759978.81185.046069981.01284.965829992.08583.6433610003.2381.26124
10014.3392.7788410024.8499.0238810025.4399.2112310047.6499.1988610058.7599.02689
10070.8498.2514210080.9697.7893510092.0697.6687210093.8397.6698310103.1798.24256
10125.9998.94027
#Mann= 3 , 0 , 0
9874.022    0.04       09874.022    0.04       010125.99    0.04       0
#XS Ineff= 2 , 0
       09890.009                       0
Bank Sta=9874.022,10125.99
Exp/Cntr=0.3,0.1

Type RM Length L Ch R = 1 ,4480.087,144.461300,144.461300,144.461300
XS GIS Cut Line= 6
 995574.20493231766831.953121998995649.309089276766861.019331148
995672.159701601766875.662583834995715.979987953766915.733618725
995750.362257808766932.855584767995793.843284932766947.880240578
#Sta/Elev= 30
9874.10695.003189883.31995.180389896.14194.980779906.737 95.33199913.55595.27295
9917.33495.363739922.90393.973349928.09692.527989939.04190.991319961.46290.33159
9973.33990.579799980.61485.800569985.925 81.8823 9994.8478.69533    999978.55642
10000.4478.59655   1000178.7583910008.4382.1274910016.6187.6186410023.35 92.3277
10027.8494.4604410040.2395.0613310051.5594.9849110062.2695.3318310073.8993.27791
10079.8892.5750810086.4592.3961110095.3793.5520510116.53   92.8910125.8992.92363
#Mann= 3 , 0 , 0
9874.106    0.04       09874.106    0.04       010125.89    0.04       0
#XS Ineff= 2 , 0
       09942.504                       0
Bank Sta=9874.106,10125.89
Exp/Cntr=0.3,0.1

Type RM Length L Ch R = 1 ,4335.625,219.657800,219.657800,219.657800
XS GIS Cut Line= 2
995534.896298521767032.531159914995836.979631864767013.433937705
#Sta/Elev= 26
9882.37390.234159902.516 90.23269922.55690.035449932.57689.606849942.59689.06009
9952.61689.010769962.63688.728479972.65688.040429982.67682.733559992.69676.57433
10002.7275.4718910012.7477.5524910022.76  79.40810032.7879.68252 10042.881.76086
10062.8487.3567210072.8689.9423210082.8891.6789610102.9292.6883210112.9491.74995
10122.9691.8518910132.9892.26806   1014394.6356510163.0494.2312110173.0694.90274
10185.0695.11414
#Mann= 3 , 0 , 0
9882.373    0.04       09882.373    0.04       010185.06    0.04       0
#XS Ineff= 2 , 0
       09942.482                       0
Bank Sta=9882.373,10185.06
Exp/Cntr=0.3,0.1