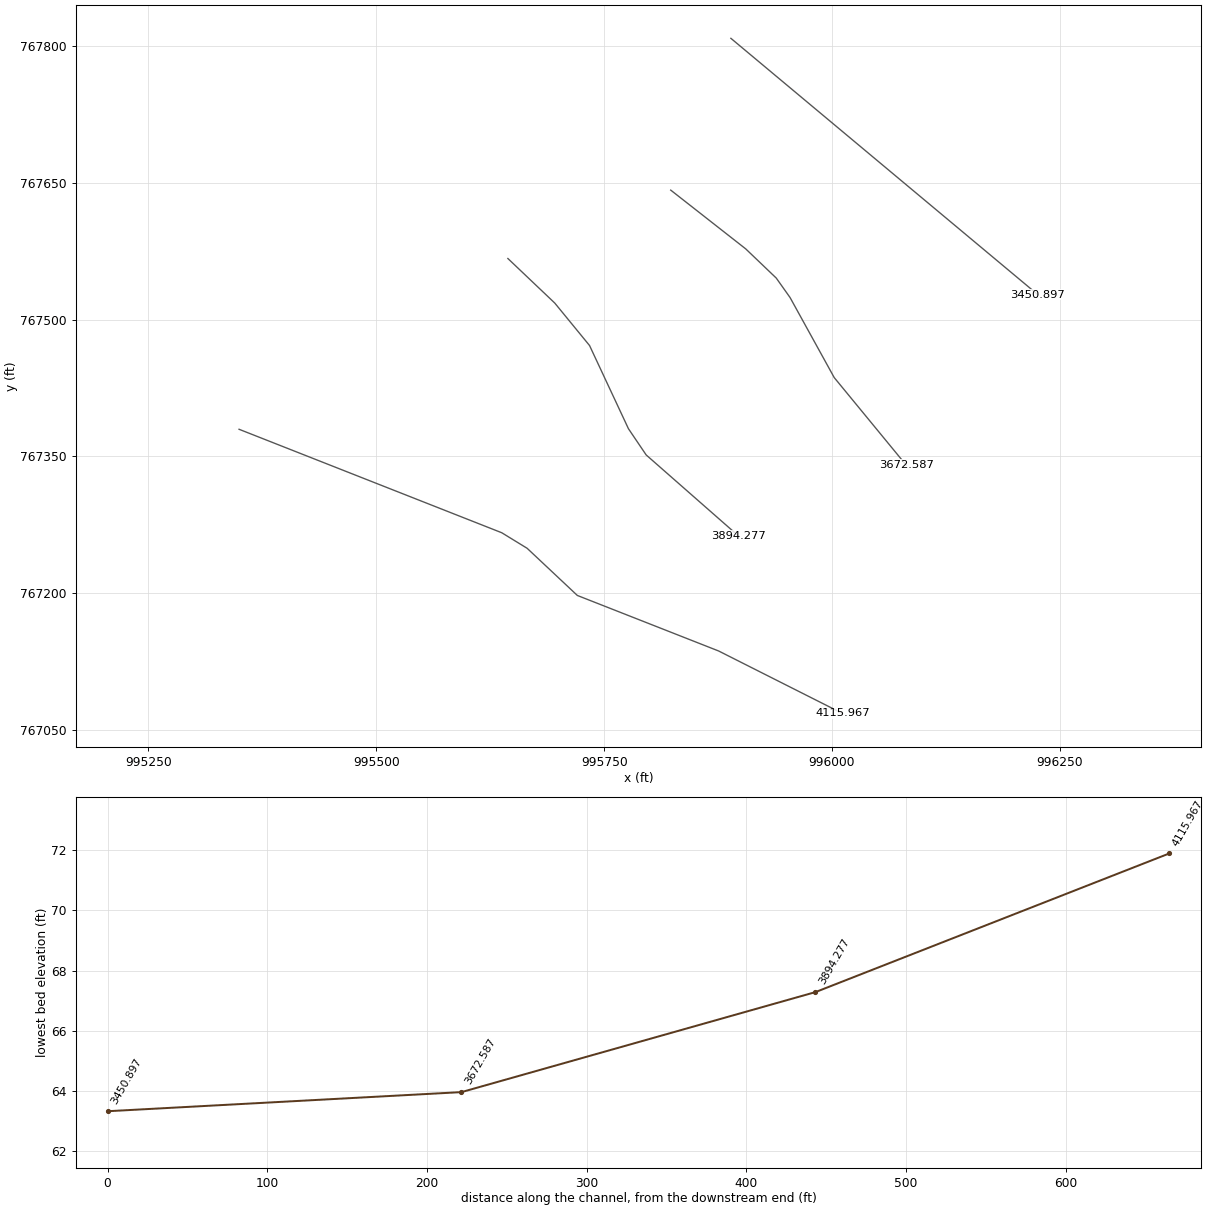
HEC-RAS study 155_ras.prj: 155

--- 155_ras.g01 (geometry) --- (continued)

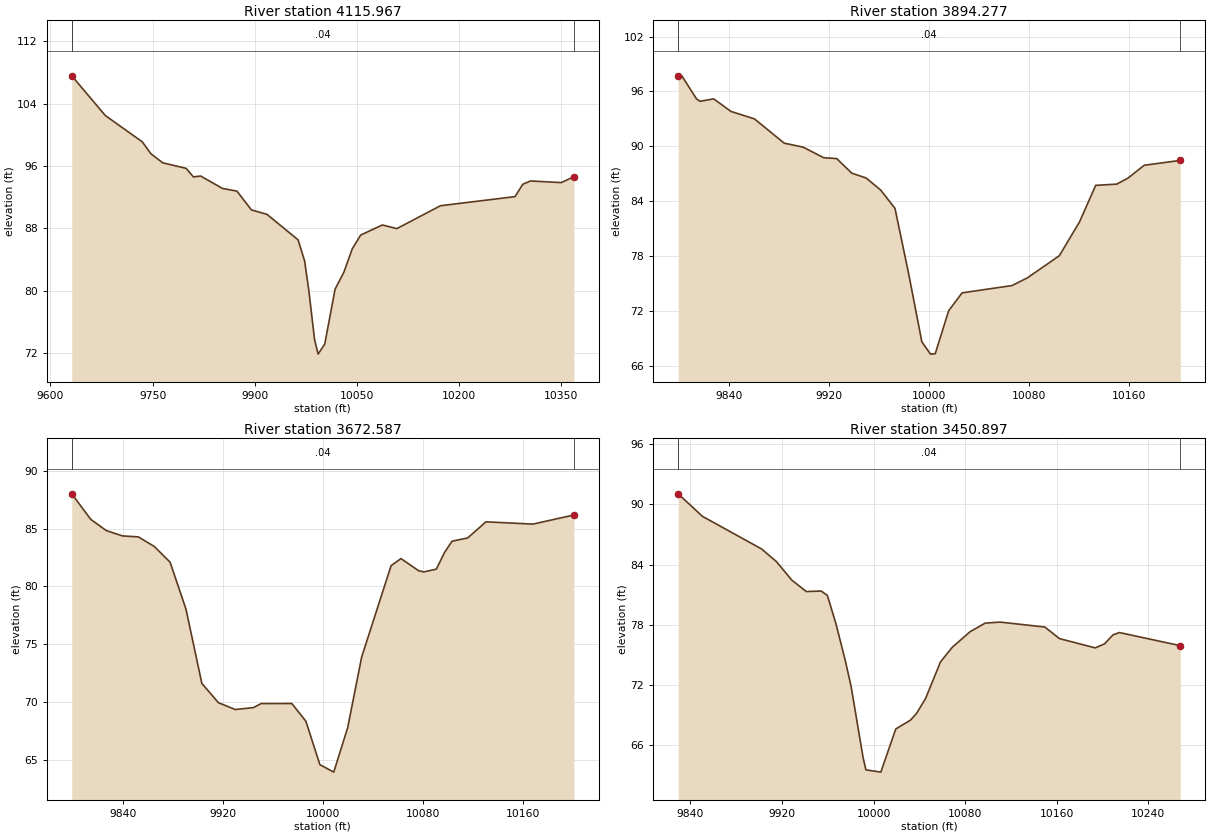
Type RM Length L Ch R = 1 ,4115.967,221.690300,221.690300,221.690300
XS GIS Cut Line= 6
 995349.42612661767379.622410156995637.664477188767266.095950266
995665.508072575767249.039064587995720.570412202767197.303502401
995875.557401931767136.393736303996011.335366214767067.909323885
#Sta/Elev= 30
9631.323107.55669680.671102.46159734.81299.102719747.66197.554659764.944 96.4098
9799.24495.697899809.90594.608119820.56794.71449 9852.5593.127679873.87392.77704
9895.19590.368939918.07889.801249963.59586.537419973.269 83.81749979.40680.04161
9987.83973.752499993.05571.8928310002.7973.18654   1001880.2285410030.9482.40044
10043.1485.3757610055.5987.15275 10087.488.44469 10108.787.9775410172.68 90.9091
10282.2292.0781310293.54 93.657810304.8694.0827310350.14 93.875910368.6394.63079
#Mann= 3 , 0 , 0
9631.323    0.04       09631.323    0.04       010368.63    0.04       0
#XS Ineff= 2 , 0
       0                               0
Bank Sta=9631.323,10368.63
Exp/Cntr=0.3,0.1

Type RM Length L Ch R = 1 ,3894.277,221.690300,221.690300,221.690300
XS GIS Cut Line= 6
995644.371614928767567.002001549995695.801310252767518.129039561
995733.988910708767471.510712282995776.660694987767380.238400311
995796.116075333767351.461230929995897.267552293767262.703360401
#Sta/Elev= 30
9799.10997.694219802.01697.704189813.77195.189629816.53294.920089827.56695.18492
9841.36193.811989860.08393.001949883.97290.343669899.09889.907679915.49788.75645
9925.97888.657819937.90787.07405  9949.586.534659961.093 85.22429972.59683.21691
9983.34276.201919994.08868.63316   1000167.28309 10004.867.3299810015.5572.02465
 10026.373.9797910066.22 74.777510078.6275.6258910104.1378.0436210120.2481.73316
10133.1985.7299910150.0985.86783 10159.186.5297410172.0587.92712 10200.988.45906
#Mann= 3 , 0 , 0
9799.109    0.04       09799.109    0.04       0 10200.9    0.04       0
#XS Ineff= 2 , 0
       0                               0
Bank Sta=9799.109,10200.9
Exp/Cntr=0.3,0.1

Type RM Length L Ch R = 1 ,3672.587,221.690300,221.690300,221.690300
XS GIS Cut Line= 6
995823.053807731 767642.03181055995905.332482556767577.562361586
995938.853303628767545.517396331995953.969948571767524.206379237
996002.430526107 767436.35503081996081.337505797767340.365106633
#Sta/Elev= 30
9799.06788.003439814.24385.800329826.68184.829389839.65184.367699852.35684.28219
 9865.0683.460089877.76482.096969890.46878.044919903.17271.626289916.46169.95486
9929.98569.368349944.44169.534569950.64669.882179975.16669.889179986.44168.35784
 9997.6364.6075310008.7463.95935 10019.967.8060410031.0673.8964210054.6281.79276
10062.5482.4085910076.5981.3654910080.8581.2558310090.8381.4943210097.4382.93978
10103.3783.90582 10115.984.1921710130.5985.5837810168.0985.3874410200.9486.17522
#Mann= 3 , 0 , 0
9799.067    0.04       09799.067    0.04       010200.94    0.04       0
#XS Ineff= 2 , 0
       0                               0
Bank Sta=9799.067,10200.94
Exp/Cntr=0.3,0.1

Type RM Length L Ch R = 1 ,3450.897,0.000000,0.000000,0.000000
XS GIS Cut Line= 2
995889.062965184767808.572826579996225.868520766767527.322826564
#Sta/Elev= 30
9829.26491.04108 9850.4488.800139902.13985.551189915.16884.288619928.44882.46034
9941.22481.309839954.25281.357729959.65180.92435 9967.2878.043259975.25274.45303
9980.30871.911199990.85464.768369993.33663.5510110006.3663.3238210019.3967.61833
10032.4268.5165210037.6669.1883110045.4570.6589310058.4874.3014710068.8675.76524
10084.4677.3174110097.5678.1644110110.5978.2657510149.6777.7755310162.47 76.6212
10193.6775.6979110201.7976.0942910209.28 76.996210214.8177.2256710268.0675.91874
#Mann= 3 , 0 , 0
9829.264    0.04       09829.264    0.04       010268.06    0.04       0
#XS Ineff= 2 , 0
       0                               0
Bank Sta=9829.264,10268.06
Exp/Cntr=0.3,0.1